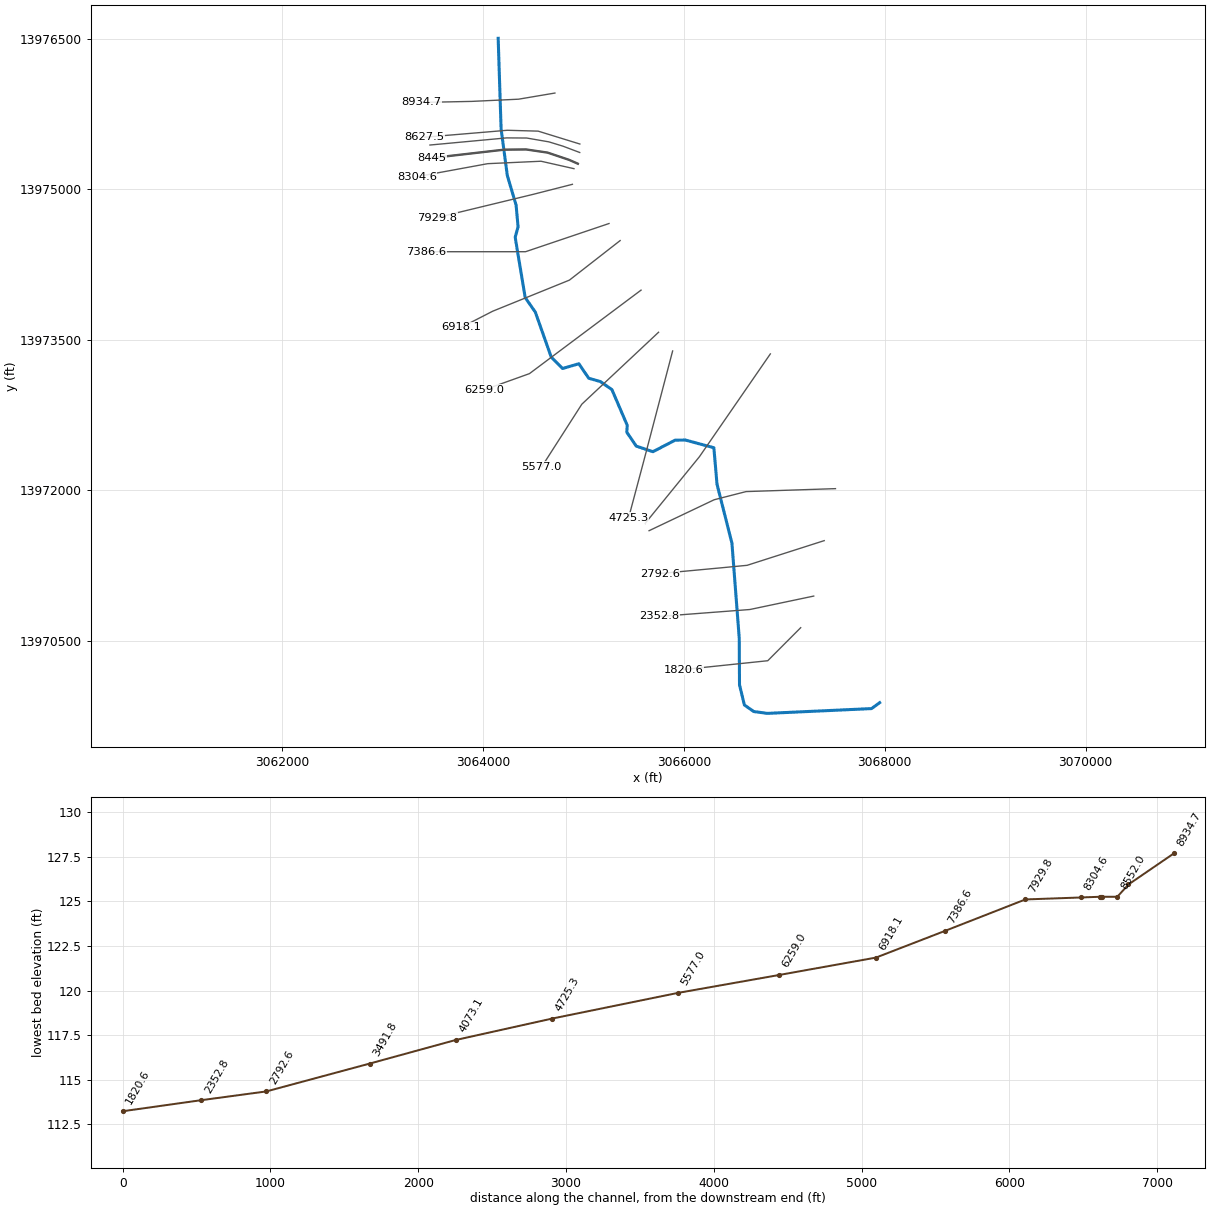
--- M104-00-00.PRJ (project) ---

Proj Title=M104-00-00
Current Plan=p03
Default Exp/Contr=.3,.1
English Units
Geom File=g01
Flow File=f03
Flow File=f02
Plan File=p02
Plan File=p03
Y Axis Title=Elevation
X Axis Title(PF)=Main Channel Distance
X Axis Title(XS)=Station
BEGIN DESCRIPTION:
Willow Creek
Tributary 2.44
HCFCD Unit M104-00-00
(Flood Hazard, Floodway) Model
10,2,1,0.2% Event
Filename: M104-00-00.prj
Prepared by: Halff Associates,Inc Date: 03/05/2004
Reviewed by:                     Date:
STATUS Final RAS
END DESCRIPTION:
DSS Export Rating Curves= 0
DSS Export Rating Curve Sorted= 0
DSS Export Volume Flow Curves= 0
DXF OffsetX= 0
DXF OffsetY= 0
DXF ScaleX= 1
DXF ScaleY= 10

--- M104-00-00.p03 (plan) ---

Plan Title=Floodway
Program Version=3.11
Short Identifier=Floodway0607
Geom File=g01
Flow File=f03
Subcritical Flow
K Sum by GR= 0
Std Step Tol= 0.01
Critical Tol= 0.01
Num of Std Step Trials= 20
Max Error Tol= 0.3
Flow Tol Ratio= 0.001
Split Flow NTrial= 30
Split Flow Tol= 0.02
Split Flow Ratio= 0.02
Log Output Level= 0
Friction Slope Method= 1
Unsteady Friction Slope Method= 2
Unsteady Bridges Friction Slope Method= 1
Parabolic Critical Depth
Global Vel Dist= 0 , 0 , 0
Global Log Level= 0
CheckData=True
Encroach Param=-1 ,0,0, 2
Encroach River=M104-00-00
Encroach Reach=M104-00-00_0018
Encroach Node=8934.7
       1  4961.2  5022.9
Encroach Node=8627.5
       1  4978.7  5042.1
Encroach Node=8552.0
       1  4972.5  5032.5
Encroach Node=8500.0
       1  4972.5  5032.5
Encroach Node=8445
       1  4972.5  5032.5
Encroach Node=8440.0
       1  4972.5  5032.5
Encroach Node=8439.0
       1  4972.5  5032.5
Encroach Node=8435.0
       1  4972.5  5032.5
Encroach Node=8304.6
       1    4935    5070
Encroach Node=7929.8
       1    4960    5100
Encroach Node=7386.6
       1    4850    5045
Encroach Node=6918.1
       1    4730    5035
Encroach Node=6259.0
       1    4790    5055
Encroach Node=5577.0
       1    4960    5080
Encroach Node=4725.3
       1  4941.7  5031.4
Encroach Node=4073.1
       1  4977.1  5075.3
Encroach Node=3491.8
       1 4946.51  5056.2
Encroach Node=2792.6
       1 4946.53 5011.51
Encroach Node=2352.8
       1 4973.28 5024.62
Encroach Node=1820.6
       1 4975.46 5022.89
Computation Interval=1HOUR
Output Interval=1HOUR
Run HTab= 0
Run UNet= 0
Run PostProcess= 0
UNET Theta= 1
UNET Theta Warmup= 1
UNET ZTol= 0.02
UNET ZSATol= 0.1
UNET MxIter= 20
UNET MaxInSteps= 20
UNET DtIC= 0
UNET DtMin= 0
UNET MaxCRTS= 20
UNET WFStab= 2
UNET SFStab= 1
UNET WFX= 1
UNET SFX= 1
UNET DSS MLevel= 4
UNET DZMax Abort= 100
UNET Convert EG Bridges=-1
UNET Use Existing IB Tables=-1
UNET Froude Reduction=False
UNET Froude Limit= 1
UNET Froude Power= 10
Instantaneous Interval=1HOUR
Write IC File= 0
Echo Input=False
Echo Output=False
Write Detailed= 0
Detailed Automatic Start=False, 10

--- M104-00-00.p02 (plan) ---

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Plan Title=FEMA Effective June 2007
Version=Version 3.0.1  Mar 2001
Short Identifier=FEMAeff0607
Geom File=g01
Flow File=f02
IC Time=0
Write Velocity= 0

--- M104-00-00.f03 (steady flow) ---

Flow Title=Floodway
Program Version=3.13
Number of Profiles= 2
Profile Names=1PCT_100yr,1PCTFloodway_100yrFW
River Rch & RM=M104-00-00,M104-00-00_0018       ,8934.7
     770     770
River Rch & RM=M104-00-00,M104-00-00_0018       ,8552.0
     890     890
River Rch & RM=M104-00-00,M104-00-00_0018       ,7929.8
     970     970
River Rch & RM=M104-00-00,M104-00-00_0018       ,6918.1
    1030    1030
River Rch & RM=M104-00-00,M104-00-00_0018       ,6259.0
    1100    1100
River Rch & RM=M104-00-00,M104-00-00_0018       ,5577.0
    1150    1150
River Rch & RM=M104-00-00,M104-00-00_0018       ,4073.1
    1180    1180
River Rch & RM=M104-00-00,M104-00-00_0018       ,3491.8
    1200    1200
River Rch & RM=M104-00-00,M104-00-00_0018       ,2792.6
    1255    1255
Boundary for River Rch & Prof#=M104-00-00,M104-00-00_0018       , 1
Up Type= 0
Dn Type= 1
Dn Known WS=124
Boundary for River Rch & Prof#=M104-00-00,M104-00-00_0018       , 2
Up Type= 0
Dn Type= 1
Dn Known WS=124
DSS Import GetInterval= 0
DSS Import GetPeak= 0
DSS Import FillOption= 0

--- M104-00-00.f02 (steady flow) ---

Flow Title=FEMA Effective June 2007
Program Version=3.13
Number of Profiles= 4
Profile Names=10PCT_10yr, 2PCT_50yr, 1PCT_100yr,0.2PCT_500yr
River Rch & RM=M104-00-00,M104-00-00_0018 ,8934.7
     390     630     770    1170
River Rch & RM=M104-00-00,M104-00-00_0018 ,8552.0
     450     710     890    1400
River Rch & RM=M104-00-00,M104-00-00_0018 ,7929.8
     490     780     970    1480
River Rch & RM=M104-00-00,M104-00-00_0018 ,6918.1
     520     840    1030    1540
River Rch & RM=M104-00-00,M104-00-00_0018 ,6259.0
     550     900    1100    1600
River Rch & RM=M104-00-00,M104-00-00_0018 ,5577.0
     570     950    1150    1700
River Rch & RM=M104-00-00,M104-00-00_0018 ,4073.1
     590     980    1180    1760
River Rch & RM=M104-00-00,M104-00-00_0018 ,3491.8
     600    1000    1200    1800
River Rch & RM=M104-00-00,M104-00-00_0018 ,2792.6
     630    1045    1255    1872
Boundary for River Rch & Prof#=M104-00-00,M104-00-00_0018 , 1
Up Type= 0
Dn Type= 1
Dn Known WS=120
Boundary for River Rch & Prof#=M104-00-00,M104-00-00_0018 , 2
Up Type= 0
Dn Type= 1
Dn Known WS=123
Boundary for River Rch & Prof#=M104-00-00,M104-00-00_0018 , 3
Up Type= 0
Dn Type= 1
Dn Known WS=124
Boundary for River Rch & Prof#=M104-00-00,M104-00-00_0018 , 4
Up Type= 0
Dn Type= 1
Dn Known WS=127
DSS Import GetInterval= 0
DSS Import GetPeak= 0
DSS Import FillOption= 0

--- M104-00-00.g01 (geometry) ---

Geom Title=M104-00-00 June 2007
Program Version=3.13

River Reach=M104-00-00      ,M104-00-00_0018
Reach XY= 30
      3064152.89     13976507.41     3064182.141     13975603.32
     3064243.773     13975139.78     3064331.365     13974843.42
     3064350.996     13974627.13      3064322.35     13974523.83
     3064421.831     13973922.17     3064522.871     13973776.44
     3064680.857     13973328.52     3064793.704      13973214.8
     3064955.836     13973262.01     3065054.121     13973117.58
     3065169.572      13973084.6     3065285.018     13973003.89
     3065437.796     13972647.12     3065432.588     13972579.41
     3065527.206     13972440.52     3065693.005     13972384.97
     3065913.491     13972499.55     3066014.667     13972501.47
     3066299.487     13972424.42     3066330.737      13972060.7
     3066479.175     13971473.03     3066552.091     13970523.38
     3066554.695     13970059.83     3066603.307     13969858.45
     3066697.057     13969793.34     3066831.605     13969775.11
     3067868.932     13969822.86      3067949.66     13969881.88

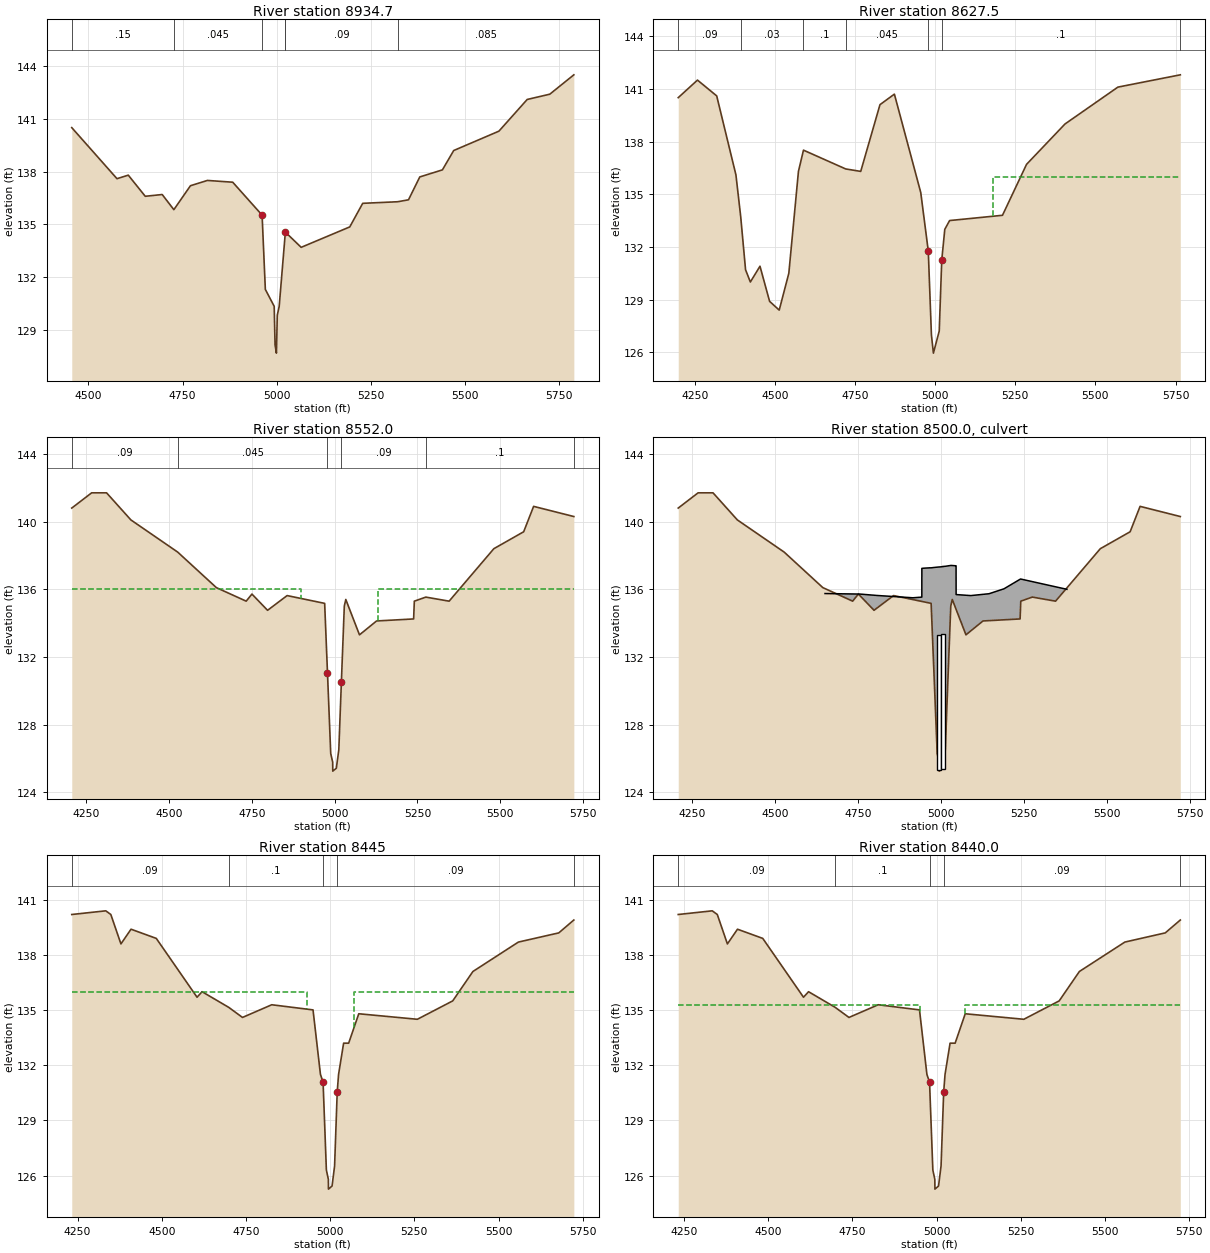
Type RM Length L Ch R = 1 ,8934.7  ,311.6,307.2,307
BEGIN DESCRIPTION:
Cross Section 8934.7
END DESCRIPTION:
XS GIS Cut Line= 4
      3064717.64      13975961.8      3064355.65      13975900.5
      3063889.73      13975878.5      3063391.04      13975868.1
#Sta/Elev= 30
  4456.1   140.5  4576.1   137.6  4606.1   137.8  4651.1   136.6  4696.1   136.7
    4727  135.84  4771.1   137.2  4816.1   137.5  4883.2   137.4  4961.2  135.53
  4969.8  131.31  4993.3  130.35  4995.6  128.15  4999.2  127.69  5001.5  129.85
  5006.6  130.35  5022.9  134.56  5023.1  134.56  5064.9   133.7  5193.8  134.86
  5228.2   136.2    5321  136.29  5349.7   136.4  5379.7   137.7  5439.7   138.1
  5469.7   139.2  5589.7   140.3  5664.7   142.1  5724.7   142.4  5788.5   143.5
#Mann= 6 ,-1 , 0
  4456.1     .15       0    4727    .045       0  4961.2     .05       0
  5022.9    .045       0  5023.1     .09       0    5321    .085       0
#XS Ineff= 2 , 0
       0    4820     137               0
Permanent Ineff=
       F       F
Bank Sta=4961.2,5022.9
Exp/Cntr=0.3,0.1

Type RM Length L Ch R = 1 ,8627.5  ,77,75.5,75.4
BEGIN DESCRIPTION:
Ineffectives used to transitioning with downstream cross sections
Cross Section XS5.5
END DESCRIPTION:
XS GIS Cut Line= 4
      3064965.76      13975453.4      3064550.93      13975581.9
      3064243.83      13975590.5        3063422.      13975521.3
#Sta/Elev= 30
  4198.7   140.5  4258.7   141.5  4318.7   140.6  4378.7   136.1  4393.6  133.72
  4408.7   130.7  4423.7     130  4453.7   130.9  4483.7   128.9  4513.7   128.4
  4543.7   130.5  4573.7   136.3  4589.4  137.51    4721  136.44    4768   136.3
    4828   140.1    4873   140.7  4955.2   135.1  4978.7  131.77  4988.5  126.99
  4994.7  125.95  5012.9  127.21  5020.7  131.24  5030.2     133  5045.2   133.5
  5210.2   133.8  5285.2   136.7  5405.2     139  5570.2   141.1  5764.9   141.8
#Mann= 7 ,-1 , 0
  4198.7     .09       0  4393.6     .03       0  4589.4      .1       0
    4721    .045       0  4978.7     .05       0  5020.7      .1       0
  5764.9      .2       0
#XS Ineff= 2 , 0
       0    4850     138    5180       0     136
Permanent Ineff=
       F       F
Bank Sta=4978.7,5020.7
Exp/Cntr=0.5,0.3

Type RM Length L Ch R = 1 ,8552.0  ,107,107,107
BEGIN DESCRIPTION:
Upstream Section of Culvert near Alderly Road
Ineffectives used for transitioning with downstream cross sections
END DESCRIPTION:
XS GIS Cut Line= 6
      3064964.43      13975368.9      3064797.56       13975432.
      3064657.75      13975474.9      3064436.76      13975513.2
       3064236.9      13975514.5      3063473.87      13975443.3
#Sta/Elev= 30
    4207   140.8    4267   141.7    4312   141.7  4385.4   140.1  4526.6   138.2
  4643.4   136.1  4733.4   135.3  4750.7  135.72  4797.9  134.76  4856.9  135.63
  4970.2  135.17  4978.7  131.08  4988.5   126.3  4994.4  125.79  4994.7  125.26
  5005.4  125.43  5012.9  126.52  5020.7  130.55  5029.5  135.01    5034   135.4
  5075.3  133.31  5126.8  134.13  5238.7  134.25  5240.8   135.3  5275.5  135.54
  5345.8   135.3  5480.8   138.4  5570.8   139.4  5600.8   140.9  5722.2   140.3
#Mann= 6 ,-1 , 0
    4207     .09       0  4526.6    .045       0  4978.7     .05       0
  5020.7     .09       0  5275.5      .1       0  5722.2      .2       0
#XS Ineff= 2 , 0
       0    4900     136    5130       0     136
Permanent Ineff=
       F       F
Bank Sta=4978.7,5020.7
Exp/Cntr=0.5,0.3

Type RM Length L Ch R = 2 ,8500.0  ,,,
BEGIN DESCRIPTION:
ALDERLY RD.
APPROX. 350' DS FROM PROJECTED ALDERLY RD
Structure ID: M104-00-00-01
END DESCRIPTION:
Bridge Culvert--1,0,-1,-1, 0
Deck Dist Width WeirC Skew NumUp NumDn MinLoCord MaxHiCord MaxSubmerge Is_Ogee
15,89,3,0, 33, 33, , , 0.95, 0, 1,1,,
    4650    4755    4805    4860    4915 4942.09  4942.2 4942.31  4949.3  4966.6
  4968.2  4970.2  4978.7  4988.5  4993.7  4994.4  4994.7  5000.9  5003.5  5005.4
  5005.5  5006.5  5012.9  5029.5    5031 5045.39  5045.5 5045.61    5090    5145
    5190    5240    5380
  135.75  135.72  135.64  135.57   135.5  135.54  137.24  137.24  137.25  137.27
  137.27  137.27  137.29  137.31  137.32  137.32  137.32  137.33  137.34  137.34
  137.35  137.35  137.36  137.41  137.41  137.39  137.39  135.69  135.63  135.74
  136.03  136.61     136
                                                                                
                          126.39  125.79  125.88  125.35  125.38  125.46  125.52
  125.89  125.91
                        
    4650    4755    4805    4860    4915 4942.09  4942.2 4942.31  4949.3  4966.6
  4968.2  4970.2  4978.7  4988.5  4993.7  4994.4  4994.7  5000.9  5003.5  5005.4
  5005.5  5006.5  5012.9  5029.5    5031 5045.39  5045.5 5045.61    5090    5145
    5190    5240    5380
  135.75  135.72  135.64  135.57   135.5  135.54  137.24  137.24  137.25  137.27
  137.27  137.27  137.29  137.31  137.32  137.32  137.32  137.33  137.34  137.34
  137.35  137.35  137.36  137.41  137.41  137.39  137.39  135.69  135.63  135.74
  136.03  136.61     136
                                                                                
                          126.39  125.79  125.88  125.35  125.38  125.46  125.52
  125.89  125.91
                        
BR Coef= 1 , 1 , 1 ,1.25, 0 ,,,0.8,0,2,0,
WSPro=,,,, 1 ,,,, 0 ,,,, 0 ,,,,-1 ,-1 ,-1 , 0 , 0 , 0 , 0 , 0
Culvert=2,8,10,89,0.015,0.4,1,8,2,125.3,4993.5,125.26,4993.5,Culvert #1  , 0 ,15
Culvert Bottom n=0.015
Culvert=2,8,10,89,0.015,0.4,1,8,2,125.36,5006.3,125.28,5006.3,Culvert #2  , 0 ,15
Culvert Bottom n=0.015
BC Design=,, 0 ,, 0 ,,,,,,
BC HTab HWMax=141.8

Type RM Length L Ch R = 1 ,8445    ,5,5,5
BEGIN DESCRIPTION:
Downstream Section of Culvert near Alderly Road
Ineffectives used for transitioning with downstream cross sections
END DESCRIPTION:
XS GIS Cut Line= 6
      3064951.77       13975260.      3064859.32      13975300.6
      3064645.09      13975372.8      3064430.89      13975404.3
      3064212.13      13975402.1      3063488.27      13975318.6
#Sta/Elev= 30
  4232.7   140.2  4333.7   140.4  4348.7   140.2  4378.7   138.6  4408.7   139.4
  4483.7   138.9  4604.7   135.7  4619.7     136  4698.7  135.15  4739.7   134.6
 4826.58  135.29 4949.17  135.01  4971.2   131.5    4979  131.08  4988.8   126.3
  4994.7  125.79    4995  125.26  5005.7  125.43  5013.2  126.52    5021  130.55
    5025   131.5    5040   133.2    5055   133.2    5085   134.8    5259   134.5
    5364   135.5    5424   137.1    5559   138.7    5679   139.2  5723.7   139.9
#Mann= 5 ,-1 , 0
  4232.7     .09       0  4698.7      .1       0    4979     .05       0
    5021     .09       0  5723.7      .2       0
#XS Ineff= 2 , 0
       0    4930     136    5070       0     136
Permanent Ineff=
       F       F
Bank Sta=4979,5021
Exp/Cntr=0.5,0.3

Type RM Length L Ch R = 1 ,8440.0  ,5,5,5
BEGIN DESCRIPTION:
Upstream Section of Pipeline
END DESCRIPTION:
XS GIS Cut Line= 6
      3064949.76      13975255.4      3064857.51      13975295.9
      3064643.92      13975367.9      3064430.55      13975399.3
       3064212.4      13975397.1      3063488.87      13975313.7
#Sta/Elev= 30
  4232.7   140.2  4333.7   140.4  4348.7   140.2  4378.7   138.6  4408.7   139.4
  4483.7   138.9  4604.7   135.7  4619.7     136  4698.7  135.15  4739.7   134.6
 4826.58  135.29 4949.17  135.01  4971.2   131.5    4979  131.08  4988.8   126.3
  4994.7  125.79    4995  125.26  5005.7  125.43  5013.2  126.52    5021  130.55
    5025   131.5    5040   133.2    5055   133.2    5085   134.8    5259   134.5
    5364   135.5    5424   137.1    5559   138.7    5679   139.2  5723.7   139.9
#Mann= 5 ,-1 , 0
  4232.7     .09       0  4698.7      .1       0    4979     .05       0
    5021     .09       0  5723.7      .2       0
#XS Ineff= 2 , 0
       0    4950   135.3    5085       0   135.3
Permanent Ineff=
       F       F
Bank Sta=4979,5021
Exp/Cntr=0.5,0.3

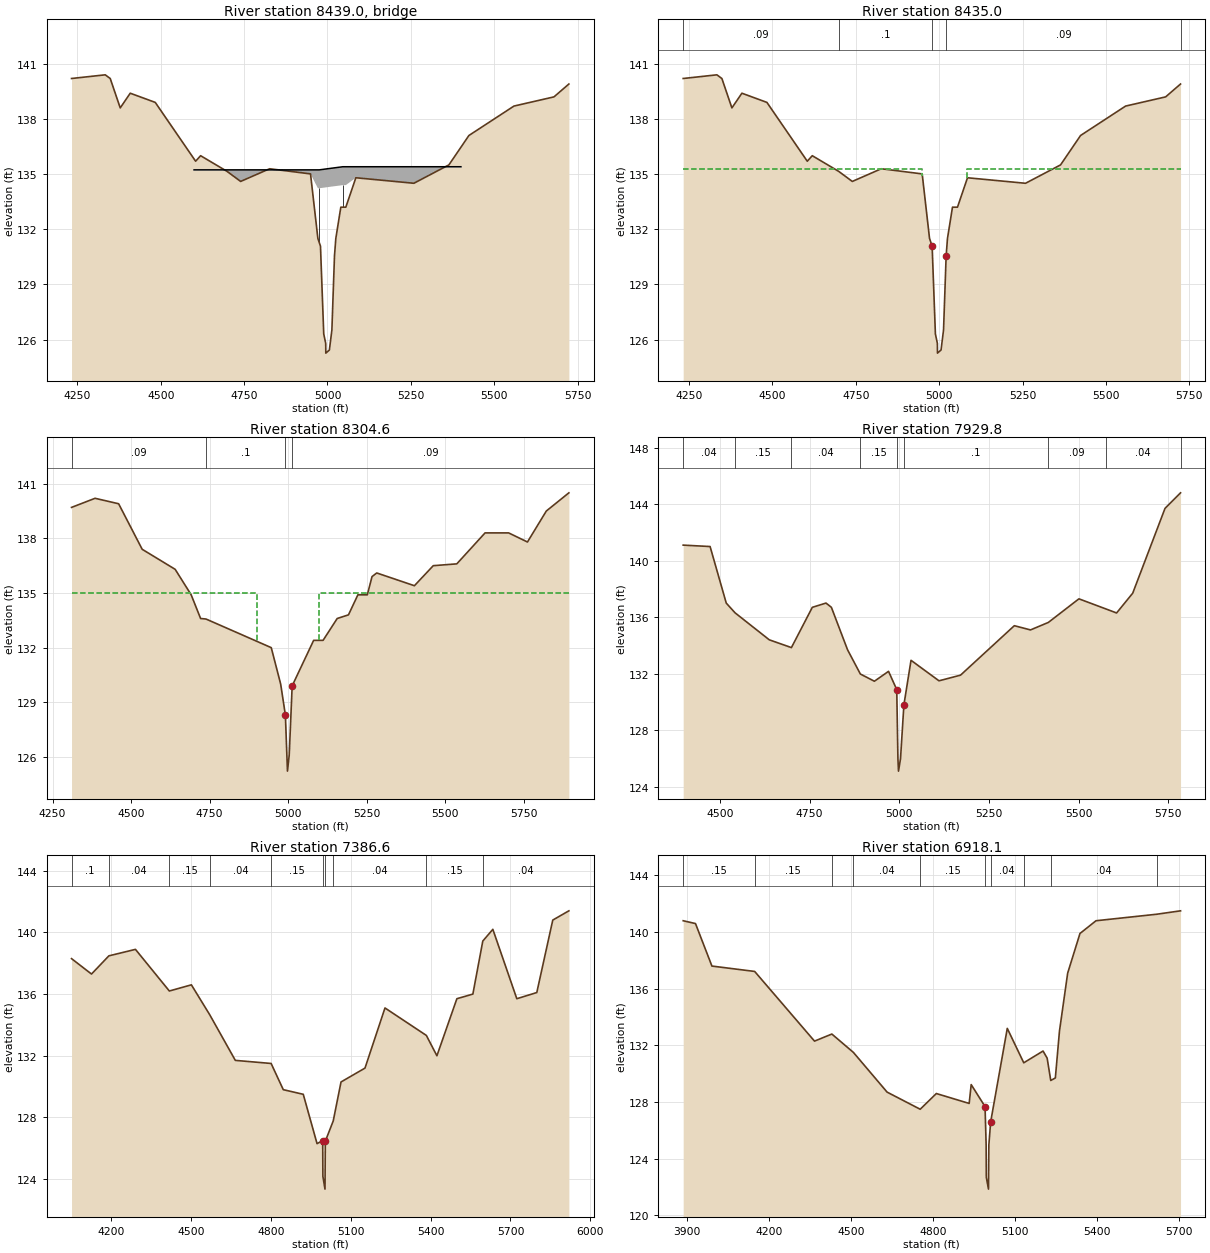
Type RM Length L Ch R = 3 ,8439.0  ,,,
BEGIN DESCRIPTION:
PL1_M104-00-00-01
END DESCRIPTION:
Bridge Culvert--1,0,-1,-1, 0
Deck Dist Width WeirC Skew NumUp NumDn MinLoCord MaxHiCord MaxSubmerge Is_Ogee
2,1,2.6,0, 4, 4, , , 0.95, 0, 1,1,,
    4600    4975    5046    5400
  135.23  135.23   135.4   135.4
  134.23  134.23   134.4   134.4
    4600    4975    5046    5400
  135.23  135.23   135.4   135.4
  134.23  134.23   134.4   134.4
Pier Skew, UpSta & Num, DnSta & Num=  ,4975, 2 ,4975, 2 , 0 , 0 , 0 ,,
     1.3     1.3
  131.08  135.49
     1.3     1.3
  131.08  135.49
Pier Skew, UpSta & Num, DnSta & Num=  ,5046, 2 ,5046, 2 , 0 , 0 , 0 ,,
     1.3     1.3
   131.2  135.84
     1.3     1.3
   131.2  135.84
BR Coef= 1 , 1 , 1 ,1.25, 0 ,,,0.8,0,2,0,
WSPro=,,,, 1 ,,,, 0 ,,,, 0 ,,,,-1 ,-1 ,-1 , 0 , 0 , 0 , 0 , 0
BC Design=,, 0 ,, 0 ,,,,,,
BC HTab HWMax=140.6

Type RM Length L Ch R = 1 ,8435.0  ,130.4,130.4,130.4
BEGIN DESCRIPTION:
Downstream Section of Pipeline
END DESCRIPTION:
XS GIS Cut Line= 6
      3064947.75      13975250.8       3064855.7      13975291.3
      3064642.75       13975363.      3064430.21      13975394.3
      3064212.68      13975392.1      3063489.47      13975308.7
#Sta/Elev= 30
  4232.7   140.2  4333.7   140.4  4348.7   140.2  4378.7   138.6  4408.7   139.4
  4483.7   138.9  4604.7   135.7  4619.7     136  4698.7  135.15  4739.7   134.6
 4826.58  135.29 4949.17  135.01  4971.2   131.5    4979  131.08  4988.8   126.3
  4994.7  125.79    4995  125.26  5005.7  125.43  5013.2  126.52    5021  130.55
    5025   131.5    5040   133.2    5055   133.2    5085   134.8    5259   134.5
    5364   135.5    5424   137.1    5559   138.7    5679   139.2  5723.7   139.9
#Mann= 5 ,-1 , 0
  4232.7     .09       0  4698.7      .1       0    4979     .05       0
    5021     .09       0  5723.7      .2       0
#XS Ineff= 2 , 0
       0    4950   135.3    5085       0   135.3
Permanent Ineff=
       F       F
Bank Sta=4979,5021
Exp/Cntr=0.5,0.3

Type RM Length L Ch R = 1 ,8304.6  ,346,374.8,385.6
BEGIN DESCRIPTION:
Cross Section 8304.6
END DESCRIPTION:
XS GIS Cut Line= 4
      3064907.23      13975207.6      3064579.48      13975281.7
      3064049.19      13975257.4      3063344.14      13975127.7
#Sta/Elev= 30
  4310.4   139.7  4385.4   140.2  4460.4   139.9  4535.4   137.4  4640.4   136.3
  4691.4   134.9  4721.4   133.6  4738.8  133.57  4946.4     132  4976.4     130
  4991.4   128.3    4998  125.22  5003.6   126.1    5013   129.9  5081.4   132.4
  5111.4   132.4  5156.4   133.6  5192.3   133.8  5222.3   134.9  5252.3   134.9
  5267.3   135.9  5282.3   136.1  5402.3   135.4  5462.3   136.5  5537.3   136.6
  5627.3   138.3  5702.3   138.3  5762.3   137.8  5822.3   139.5  5894.2   140.5
#Mann= 4 ,-1 , 0
  4310.4     .09       0  4738.8      .1       0  4991.4     .05       0
    5013     .09       0
#XS Ineff= 2 , 0
       0    4900     135    5100       0     135
Permanent Ineff=
       F       F
Bank Sta=4991.4,5013
Exp/Cntr=0.3,0.1

Type RM Length L Ch R = 1 ,7929.8  ,532.4,543.2,505.8
BEGIN DESCRIPTION:
Cross Section 7929.8
END DESCRIPTION:
XS GIS Cut Line= 3
      3064891.62      13975051.5      3064505.96      13974952.7
       3063545.5      13974719.8
#Sta/Elev= 30
  4397.8   141.1  4472.8     141  4517.8     137  4542.4  136.31  4637.8   134.4
  4699.5  133.85  4757.8   136.7  4795.9     137  4810.9   136.7  4855.9   133.7
  4891.7  131.98  4930.8  131.47  4970.2  132.17  4993.1  130.88  4996.4  125.97
    4998  125.11  5003.6  125.99    5013  129.79  5032.9  132.95  5110.9   131.5
  5170.9   131.9  5320.9   135.4  5365.9   135.1  5415.7  135.63  5500.9   137.3
  5576.6  136.58  5605.9   136.3  5650.9   137.7  5740.9   143.7  5784.2   144.8
#Mann= 9 ,-1 , 0
  4397.8     .04       0  4542.4     .15       0  4699.5     .04       0
  4891.7     .15       0  4993.1     .07       0    5013      .1       0
  5415.7     .09       0  5576.6     .04       0  5784.2      .2       0
#XS Ineff= 2 , 0
       0    4789     135               0
Permanent Ineff=
       F       F
Bank Sta=4993.1,5013
Exp/Cntr=0.3,0.1

Type RM Length L Ch R = 1 ,7386.6  ,436.6,468.5,506.6
BEGIN DESCRIPTION:
Cross Section 7386.6
END DESCRIPTION:
XS GIS Cut Line= 3
      3065255.98      13974660.5       3064425.5      13974379.4
      3063434.97      13974379.4
#Sta/Elev= 30
    4052   138.3    4127   137.3  4192.2  138.48    4292   138.9  4419.2   136.2
    4502   136.6  4571.2  134.65    4667   131.7  4801.4   131.5    4847   129.8
    4922   129.5  4973.8   126.3    4995   126.5  4995.7  124.18  5003.6  123.35
  5004.9  126.46  5034.5  127.77  5063.8   130.3  5153.8   131.2  5228.8   135.1
  5384.1  133.32  5423.8     132  5498.8   135.7  5558.8     136  5596.1  139.44
  5633.8   140.2  5723.8   135.7  5798.8   136.1  5858.8   140.8  5919.3   141.4
#Mann= 10 ,-1 , 0
    4052      .1       0  4192.2     .04       0  4419.2     .15       0
  4571.2     .04       0  4801.4     .15       0    4995     .07       0
  5004.9      .1       0  5034.5     .04       0  5384.1     .15       0
  5596.1     .04       0
Bank Sta=4995,5004.9
Exp/Cntr=0.3,0.1

Type RM Length L Ch R = 1 ,6918.1  ,606.6,659.1,657.7
BEGIN DESCRIPTION:
Cross Section 6918.1
END DESCRIPTION:
XS GIS Cut Line= 4
      3065366.79      13974490.4      3064862.19      13974096.2
      3064099.09      13973786.2       3063784.3      13973624.5
#Sta/Elev= 30
  3887.7   140.8  3932.7   140.6  3992.7   137.6    4149  137.22  4367.7   132.3
  4431.1   132.8    4510   131.5    4633   128.7    4754  127.49    4813   128.6
    4933   127.9  4940.4  129.23    4991  127.68    4995     125  4995.7  122.68
  5003.6  121.85  5004.9  124.96  5011.5  126.59  5072.3   133.2  5132.5  130.77
    5203   131.6    5218   131.1  5231.2  129.52    5248   129.7    5263     133
    5293   137.1    5338   139.9  5396.6   140.8  5618.8  141.26  5705.6   141.5
#Mann= 10 ,-1 , 0
  3887.7     .15       0    4149     .15       0  4431.1      .1       0
    4510     .04       0    4754     .15       0    4991     .07       0
  5011.5     .04       0  5132.5      .1       0  5231.2     .04       0
  5618.8     .15       0
#XS Ineff= 2 , 0
       0                    5070       0     132
Permanent Ineff=
       F       F
Bank Sta=4991,5011.5
Exp/Cntr=0.3,0.1

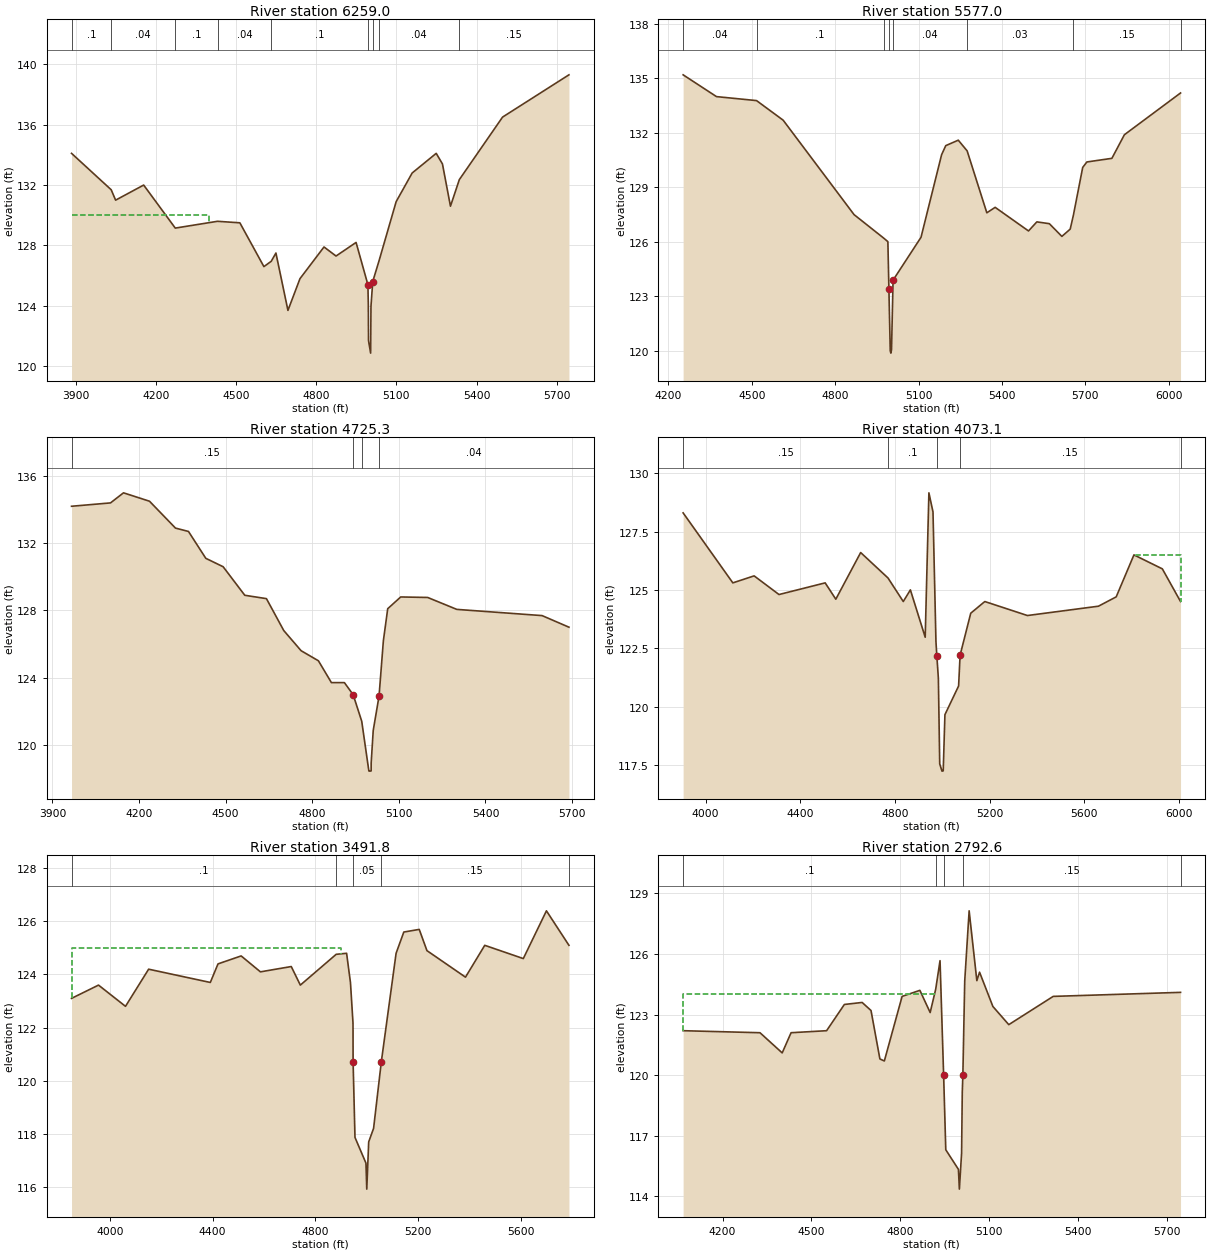
Type RM Length L Ch R = 1 ,6259.0  ,544.6,682,558.1
BEGIN DESCRIPTION:
Cross Section 6259.0
END DESCRIPTION:
XS GIS Cut Line= 3
      3065574.91      13973996.3      3064464.19      13973163.5
      3064018.62      13973003.3
#Sta/Elev= 30
  3884.1   134.1  4032.5  131.69  4049.1     131  4154.1     132  4272.4  129.15
  4430.5   129.6  4514.1   129.5  4604.1   126.6  4631.5  126.95  4649.1   127.5
  4694.1   123.7  4739.1   125.8  4829.1   127.9  4874.1   127.3  4949.1   128.2
  4993.4   125.4    4995  124.02  4995.7   121.7  5003.6  120.87  5004.9  123.98
  5011.5  125.61  5034.5  126.95  5099.1   130.9  5159.1   132.8  5249.1   134.1
  5272.4   133.4  5302.4   130.6  5335.6  132.36  5497.4   136.5  5745.9   139.3
#Mann= 9 ,-1 , 0
  3884.1      .1       0  4032.5     .04       0  4272.4      .1       0
  4430.5     .04       0  4631.5      .1       0  4993.4     .07       0
  5011.5      .1       0  5034.5     .04       0  5335.6     .15       0
#XS Ineff= 2 , 0
       0    4400     130               0
Permanent Ineff=
       F       F
Bank Sta=4993.4,5011.5
Exp/Cntr=0.3,0.1

Type RM Length L Ch R = 1 ,5577.0  ,768.9,851.7,923.7
BEGIN DESCRIPTION:
Cross Section 5577.0
END DESCRIPTION:
XS GIS Cut Line= 3
      3065749.14      13973576.1      3064985.61      13972858.7
       3064585.9      13972233.6
#Sta/Elev= 30
  4252.7   135.2  4372.7     134  4516.9  133.78  4612.7   132.7  4867.7   127.5
  4974.8   126.2  4989.4  126.01  4993.1  123.39  4997.9     120  5000.2  119.87
  5002.5  120.06  5008.1  123.89  5108.6  126.25  5182.7   130.8  5197.7   131.3
  5242.7   131.6  5274.6  131.01  5345.4   127.6  5375.4   127.9  5495.4   126.6
  5525.4   127.1  5570.4     127  5615.4   126.3  5645.4   126.7  5656.9  127.47
  5690.4   130.1  5705.4   130.4  5795.4   130.6  5840.4   131.9  6042.4   134.2
#Mann= 8 ,-1 , 0
  4252.7     .04       0  4516.9      .1       0  4974.8     .04       0
  4993.1     .07       0  5008.1     .04       0  5274.6     .03       0
  5656.9     .15       0  6042.4      .2       0
#XS Ineff= 2 , 0
       0                    5230       0     130
Permanent Ineff=
       F       F
Bank Sta=4993.1,5008.1
Exp/Cntr=0.3,0.1

Type RM Length L Ch R = 1 ,4725.3  ,636.1,652.2,608.8
BEGIN DESCRIPTION:
Cross Section 4725.3
END DESCRIPTION:
XS GIS Cut Line= 3
      3065889.14      13973389.5    3065599.9773   13972284.9635
      3065450.62      13971723.6
#Sta/Elev= 30
  3966.4   134.2  4101.4   134.4  4146.4     135  4236.4   134.5  4326.4   132.9
  4371.4   132.7  4431.4   131.1  4491.4   130.6  4566.4   128.9  4641.4   128.7
  4701.4   126.8  4761.4   125.6  4821.4     125  4866.4   123.7  4911.4   123.7
  4941.7  122.98  4971.4   121.4  4996.1  118.44  4998.8  118.43    5004  118.44
  5004.1  118.92  5011.2  120.85  5031.4   122.9  5046.4   126.2  5061.4   128.1
  5106.4   128.8 5199.77  128.77 5300.59  128.06 5596.01  127.69 5689.05     127
#Mann= 4 ,-1 , 0
  3966.4     .15       0  4941.7     .04       0  4971.4     .07       0
  5031.4     .04       0
Bank Sta=4941.7,5031.4
Exp/Cntr=0.3,0.1

Type RM Length L Ch R = 1 ,4073.1  ,601.8,581.3,521.7
BEGIN DESCRIPTION:
Cross Section 4073.1
END DESCRIPTION:
XS GIS Cut Line= 3
      3066861.49      13973360.1      3066155.95       13972335.
      3065615.91      13971669.9
#Sta/Elev= 30
  3905.3   128.3  4115.3   125.3  4205.3   125.6  4310.3   124.8  4505.3   125.3
  4550.3   124.6  4655.3   126.6  4770.7  125.51  4835.3   124.5  4865.3     125
  4927.9  122.97  4943.5  129.16  4960.8  128.34  4973.3  122.78  4977.1  122.16
  4983.5  121.21  4989.2  117.54  4998.8  117.23    5004  117.24  5011.2  119.65
    5069  120.88  5075.3   122.2  5120.3     124  5179.7   124.5  5359.7   123.9
  5659.7   124.3  5734.7   124.7  5809.7   126.5  5929.7   125.9  6006.5   124.5
#Mann= 5 ,-1 , 0
  3905.3     .15       0  4770.7      .1       0  4977.1     .07       0
  5075.3     .15       0  6006.5      .2       0
#XS Ineff= 2 , 0
       0    4946   126.5    5820       0   126.5
Permanent Ineff=
       F       F
Bank Sta=4977.1,5075.3
Exp/Cntr=0.3,0.1

Type RM Length L Ch R = 1 ,3491.8  ,699.2,699.2,699.2
BEGIN DESCRIPTION:
Cross Section 3491.8
END DESCRIPTION:
XS GIS Cut Line= 4
      3067509.72      13972016.4      3066619.87       13971987.
      3066302.57      13971905.6      3065654.69       13971597.
#Sta/Elev= 30
  3850.9   123.1  3955.9   123.6  4060.9   122.8  4150.9   124.2  4390.9   123.7
  4420.9   124.4  4510.9   124.7  4585.9   124.1  4705.9   124.3  4741.2   123.6
  4880.6  124.76  4921.2   124.8  4936.2   123.7  4946.1  122.17 4946.51   120.7
  4953.8  117.86  4996.5  116.89  4999.7  115.91  5007.2  117.69  5026.2   118.2
  5056.2   120.7  5113.8   124.8  5143.8   125.6  5203.8   125.7  5233.8   124.9
  5383.8   123.9  5458.8   125.1  5608.8   124.6  5698.8   126.4  5786.4   125.1
#Mann= 5 ,-1 , 0
  3850.9      .1       0  4880.6      .1       0 4946.51     .05       0
  5056.2     .15       0  5786.4      .2       0
#XS Ineff= 2 , 0
       0    4900     125    5150       0     125
Permanent Ineff=
       F       F
Bank Sta=4946.51,5056.2
Exp/Cntr=0.3,0.1

Type RM Length L Ch R = 1 ,2792.6  ,440.5,439.8,439
BEGIN DESCRIPTION:
Cross Section 2792.6
END DESCRIPTION:
XS GIS Cut Line= 4
      3067397.76      13971497.9      3066630.08      13971251.7
      3066382.55      13971227.8      3065760.16      13971169.5
#Sta/Elev= 30
  4066.7   122.2  4326.3   122.1  4401.3   121.1  4431.3   122.1  4551.3   122.2
  4611.3   123.5  4671.3   123.6  4701.3   123.2  4731.3   120.8  4746.3   120.7
  4806.3   123.9  4866.3   124.2  4901.1   123.1  4919.8  124.26  4934.4  125.67
 4946.53     120  4953.8   116.3  4996.5  115.33  4999.7  114.35  5007.2  116.13
  5009.5  119.14 5011.51  120.01  5017.8  124.66  5032.7  128.14  5058.7  124.68
  5067.9   125.1  5112.9   123.4  5166.6   122.5  5316.6   123.9  5746.7   124.1
#Mann= 5 ,-1 , 0
  4066.7      .1       0  4919.8      .1       0 4946.53     .05       0
 5011.51     .15       0  5746.7      .2       0
#XS Ineff= 2 , 0
       0    4920     124    5050       0     124
Permanent Ineff=
       F       F
Bank Sta=4946.53,5011.51
Exp/Cntr=0.3,0.1

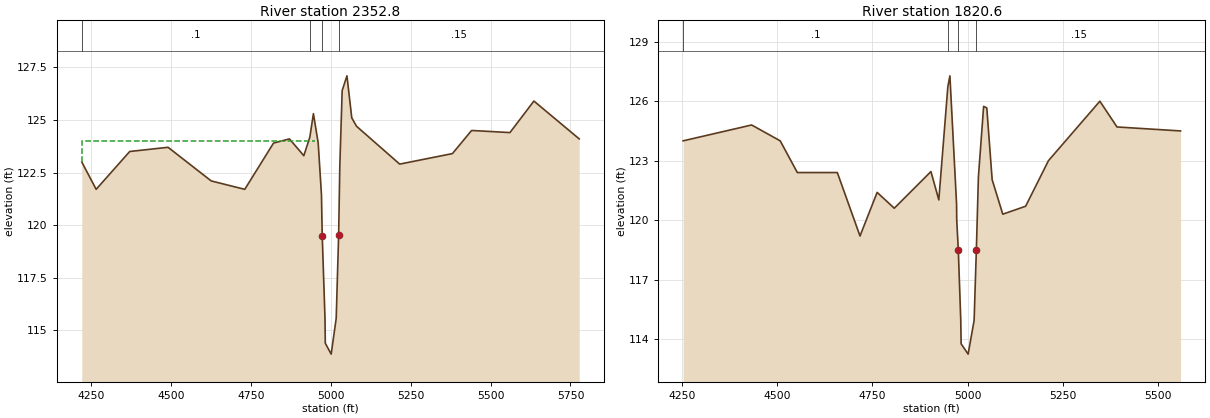
Type RM Length L Ch R = 1 ,2352.8  ,530.4,532.2,532.2
BEGIN DESCRIPTION:
Cross Section 2352.8
END DESCRIPTION:
XS GIS Cut Line= 3
      3067293.26       13970945.      3066657.42      13970810.9
       3065753.4      13970741.7
#Sta/Elev= 30
  4220.9     123  4265.9   121.7  4370.9   123.5  4490.9   123.7  4625.9   122.1
  4730.9   121.7  4820.9   123.9  4870.7   124.1  4915.7   123.3  4934.5  124.18
  4945.7   125.3  4960.7   123.9  4970.9  121.44 4973.28   119.5  4981.9  115.58
  4982.9  114.38  5001.3  113.86    5017  115.56 5024.62  119.51  5028.3   122.8
  5035.7   126.4  5050.7   127.1  5065.7   125.1  5080.7   124.7  5215.7   122.9
  5380.7   123.4  5440.7   124.5  5560.7   124.4  5635.7   125.9  5777.4   124.1
#Mann= 4 ,-1 , 0
  4220.9      .1       0  4934.5      .1       0 4973.28     .05       0
 5024.62     .15       0
#XS Ineff= 2 , 0
       0    4950     124    5050       0     124
Permanent Ineff=
       F       F
Bank Sta=4973.28,5024.62
Exp/Cntr=0.3,0.1

Type RM Length L Ch R = 1 ,1820.6  ,0,0,0
BEGIN DESCRIPTION:
Cross Section 1820.6
END DESCRIPTION:
XS GIS Cut Line= 3
      3067163.47      13970629.6      3066835.82      13970300.2
       3065998.5      13970212.6
#Sta/Elev= 30
  4252.7     124  4432.7   124.8  4507.7     124  4552.7   122.4  4657.7   122.4
  4717.3   119.2  4762.3   121.4  4807.3   120.6  4903.6  122.45  4924.3  121.02
    4948  126.73  4953.4  127.28  4970.9  120.82 4971.33  120.01 4975.46   118.5
  4981.9  114.96  4982.9  113.76  5001.3  113.24    5017  114.94 5022.89   118.5
  5028.3  122.18    5042  125.74  5050.3  125.66  5064.4  122.04  5092.3   120.3
  5152.3   120.7  5212.3     123  5347.3     126  5392.3   124.7  5559.2   124.5
#Mann= 4 ,-1 , 0
  4252.7      .1       0    4948      .1       0 4975.46     .05       0
 5022.89     .15       0
#XS Ineff= 2 , 0
       0    4950     124    5050       0     124
Permanent Ineff=
       F       F
Bank Sta=4975.46,5022.89
Exp/Cntr=0.3,0.1

Chan Stop Cuts=-1
Use User Specified Reach Order=0
User Specified Reach Order=M104-00-00      ,Reach - 1